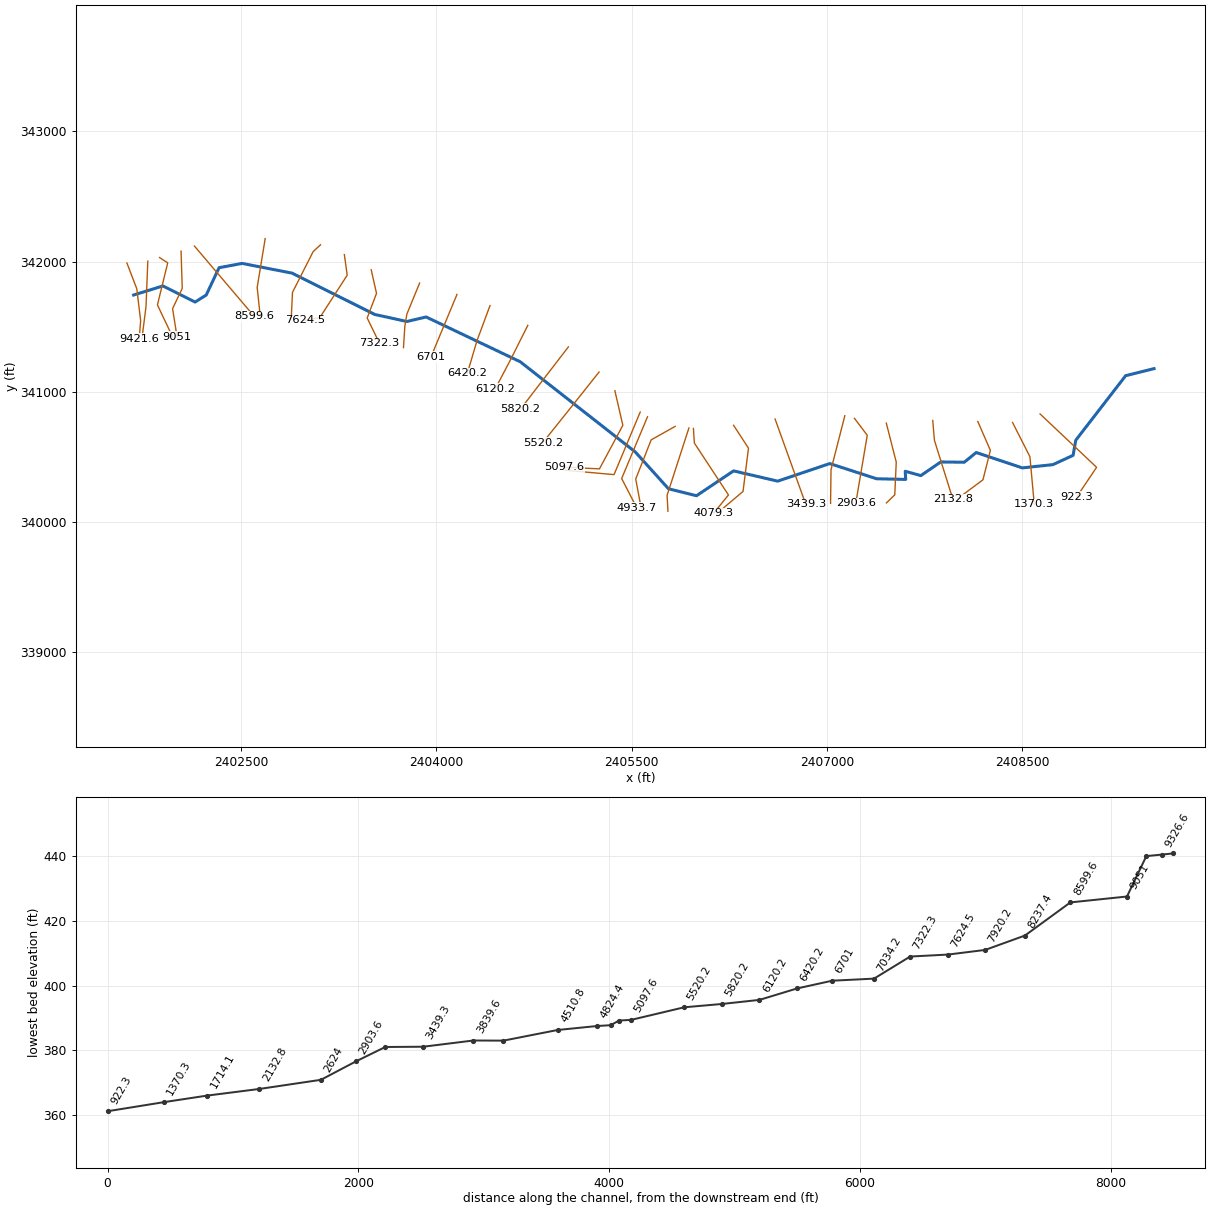
--- EVANSRUN2.prj (project) ---

Proj Title=EVANSRUN2
Current Plan=p01
Default Exp/Contr=0,0
English Units
Geom File=g01
Flow File=f01
Plan File=p01
BEGIN DESCRIPTION:
END DESCRIPTION:
DSS Export Rating Curves= 0
DSS Export Rating Curve Sorted= 0
DSS Export Volume Flow Curves= 0
DXF OffsetX= 0
DXF OffsetY= 0
DXF ScaleX= 0
DXF ScaleY= 0

--- EVANSRUN2.p01 (plan) ---

Plan Title=Floodplain
Program Version=4.00
Geom File=g01
Flow File=f01
K Sum by GR=0
Std Step Tol=0.01
Critical Tol=0.01
Num of Std Step Trials=20
Max Error Tol=0.3
Flow Tol Ratio=0.001
Split Flow NTrial=30
Split Flow Tol=0.02
Split Flow Ratio=0.02
Log Output Level=0
Friction Slope Method=1
Unsteady Friction Slope Method=2
Unsteady Bridges Friction Slope Method=1
Global Log Level=0
CheckData=False
Run HTab=0
Run UNet=0
Run PostProcess=0
UNET Theta=0
UNET Theta Warmup=0
UNET ZTol=0
UNET ZSATol=0
UNET MxIter=0
UNET MaxInSteps=0
UNET DtIC=0
UNET DtMin=0
UNET MaxCRTS=0
UNET WFStab=0
UNET SFStab=0
UNET WFX=0
UNET SFX=0
UNET DSS MLevel=0
UNET DZMax Abort=0
UNET Convert EG Bridges=0
UNET Use Existing IB Tables=0
UNET Froude Limit=0
UNET Froude Power=0
Write IC File=0
Echo Input=False
Echo Output=False
Write Detailed=0

--- EVANSRUN2.f01 (steady flow) ---

Flow Title=NFF Regression Equation
Program Version=4.10
Number of Profiles= 1
Profile Names=P100yr
River Rch & RM=EVANSRUN2,Main            ,9421.6
1366.351
River Rch & RM=EVANSRUN2,Main            ,7034.2
1441.292
River Rch & RM=EVANSRUN2,Main            ,451.2
1591.317
River Rch & RM=EVANSRUN2,Main            ,204
 1611.24
Boundary for River Rch & Prof#=EVANSRUN2,Main            , 1
Up Type= 0
Dn Type= 3
Dn Slope=0.0027
Set Internal Change=EVANSRUN2       ,Main            ,9421.6  , 1 , 3 ,453.8
DSS Import GetInterval= 0
DSS Import GetPeak= 0
DSS Import FillOption= 0

--- EVANSRUN2.g01 (geometry) ---

Geom Title=USGS 10m DEM
Program Version=4.10

River Reach=EVANSRUN2       ,Main
Reach XY= 30
     2401674.736       341742.54     2401900.031      341812.453
     2402147.325      341688.626     2402232.394      341742.445
     2402331.352      341952.515     2402508.436      341985.501
     2402892.116      341910.848     2403527.533       341593.14
     2403774.061       341539.32      2403921.63      341574.043
     2404643.852      341230.293     2405527.533      340537.584
     2405782.741      340254.598     2405998.019      340200.779
     2406282.741      340391.751     2406621.804      340312.932
     2407021.708      340448.035     2407380.936      340331.386
     2407604.894      340326.178     2407601.422      340388.678
     2407721.214      340355.692     2407874.236      340460.307
     2408054.547      340458.123     2408146.561      340532.775
     2408500.727       340414.72      2408735.97      340439.893
     2408890.484      340511.074     2408911.318      340627.393
     2409294.638      341123.379     2409512.483      341177.274

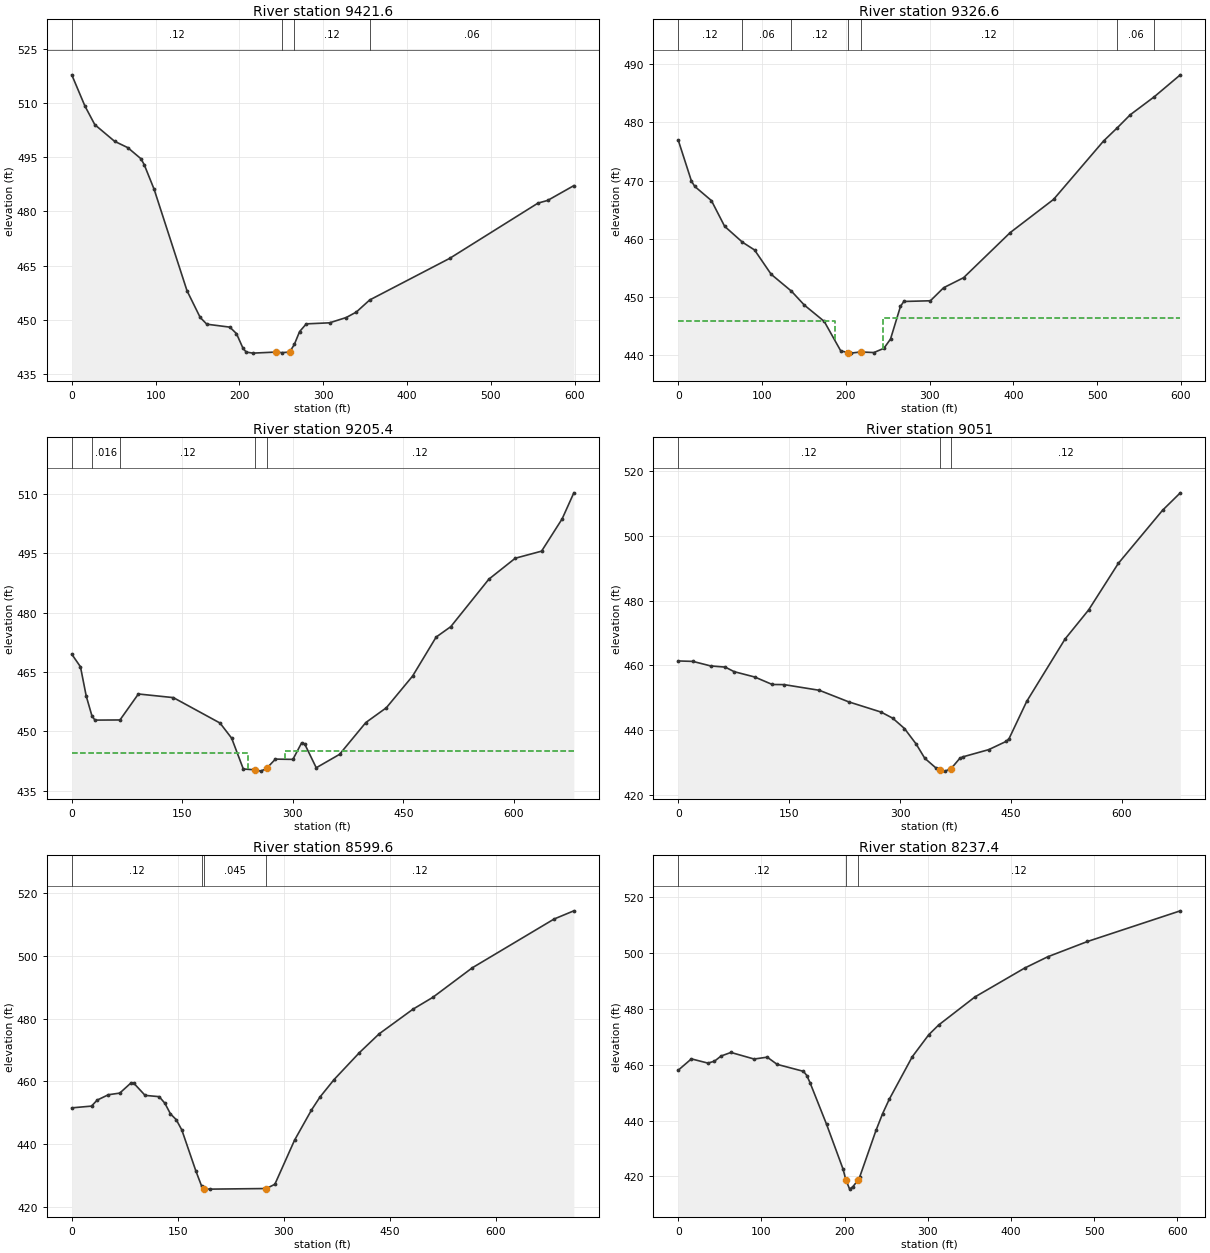
Type RM Length L Ch R = 1 ,9421.6  ,98.3,94.9,82.9
XS GIS Cut Line= 4
     2401623.267      341988.613     2401699.307      341790.524
     2401728.913       341545.69     2401717.668      341405.931
#Sta/Elev= 30
       0  517.78    15.7  509.14    27.5  503.98    51.1  499.38    66.8  497.63
    82.5  494.56    86.4  492.93    98.2  486.13   137.5  458.01   153.2  450.63
   161.1  448.76   188.6  447.94   196.5  446.15   204.3  442.09   208.2  441.03
   216.2  440.75     244  441.05   250.5  440.88   259.9  441.05   265.5  443.14
   271.8  446.71   279.8  448.85   307.6  449.14   327.5  450.61   339.5  452.12
   355.4  455.46   450.8  466.97   556.2  482.27   567.8  483.02     599  487.11
#Mann= 4 ,-1 , 0
       0     .12       0   250.5    .045       0   265.5     .12       0
   355.4     .06       0
Bank Sta=244,259.9
XS Rating Curve= 0 ,0
Exp/Cntr=0.3,0.1

Type RM Length L Ch R = 1 ,9326.6  ,126.5,121.3,119.5
XS GIS Cut Line= 3
     2401783.879       342002.93     2401770.122      341654.704
     2401738.473      341405.929
#Sta/Elev= 30
       0  476.95    15.8   469.9    19.8  468.99    39.6  466.57    55.4  462.15
   76.61 459.429    91.1  458.09   110.9  453.92  135.08451.0232   150.5  448.63
   174.2  445.84     194  440.76   203.1  440.46   205.9  440.38   217.8  440.58
   233.6  440.48   245.5  441.21   253.4   442.8   265.3  448.42   269.3  449.25
     301  449.37   316.8  451.61   340.6  453.33   396.3  461.08     448  466.77
   507.7   476.8  524.32479.1018   539.6  481.31  568.07484.3755   599.3  488.16
#Mann= 7 ,-1 , 0
       0     .12       0   76.61     .06       0  135.08     .12       0
   203.1    .045       0   217.8     .12       0  524.32     .06       0
  568.07     .12       0
#XS Ineff= 2 , 0
          186.92  445.88  244.58          446.33
Permanent Ineff=
       F       F
Bank Sta=203.1,217.8
XS Rating Curve= 0 ,0
Exp/Cntr=0.3,0.1

Type RM Length L Ch R = 1 ,9205.4  ,158.5,154.3,149.5
XS GIS Cut Line= 4
     2401874.205      342030.255     2401936.789      341989.774
     2401857.796      341666.857     2401975.275      341418.846
#Sta/Elev= 30
       0  469.48    11.8   466.3    19.6  458.91   27.36453.8912    31.4  452.81
   65.44452.8532    90.4  459.42   137.9   458.5   201.2  452.07     217  448.24
   232.8  440.45   248.7  440.24   256.6  439.91   264.5  440.62   276.4  442.95
   300.1  442.88     312  447.07     316  446.82   331.8  440.76   363.4  444.15
   399.1   452.2   426.9  455.93   462.6  463.96   494.5  473.81   514.4  476.45
   566.1  488.46   601.9  493.75   637.6  495.54   665.5   503.7   681.4  510.29
#Mann= 5 ,-1 , 0
       0     .06       0   27.36    .016       0   65.44     .12       0
   248.7    .045       0   264.5     .12       0
#XS Ineff= 2 , 0
          239.83  444.59  289.68          445.05
Permanent Ineff=
       F       F
Bank Sta=248.7,264.5
XS Rating Curve= 0 ,0
Exp/Cntr=0.3,0.1

Type RM Length L Ch R = 1 ,9051    ,424.8,451.4,477.9
XS GIS Cut Line= 4
     2402039.285      342080.195     2402048.334      341794.027
     2401974.115      341637.777     2402008.598      341420.663
#Sta/Elev= 30
       0  461.39    19.9  461.25    43.7  459.86    63.6  459.49    75.6  458.09
   103.4  456.45   127.2  454.14   143.2   454.1   190.9  452.35   230.6  448.79
   274.4  445.64   290.2  443.75     306  440.58   321.7  435.84   333.5  431.41
   349.2  428.31   354.1   427.9     361  427.46   369.1  428.24   380.7  431.36
   384.6  431.83     420  434.08   443.6  436.62   447.5  437.48   471.3  448.92
   523.2  468.14   555.2  477.13   595.2  491.42   655.2  507.82   679.1  513.16
#Mann= 3 ,-1 , 0
       0     .12       0   354.1    .045       0   369.1     .12       0
Bank Sta=354.1,369.1
XS Rating Curve= 0 ,0
Exp/Cntr=0.3,0.1

Type RM Length L Ch R = 1 ,8599.6  ,381.9,362.3,342.7
XS GIS Cut Line= 2
     2402141.763      342119.009     2402601.691      341578.133
#Sta/Elev= 30
       0  451.56    27.9  452.12    35.9  454.03    51.8  455.75    67.8  456.26
    83.8  459.52    87.8   459.4   103.7  455.54   123.6  455.13   131.6  453.06
   139.6  449.63   147.6  447.83   155.6  444.53   175.5  431.43  183.48426.6811
   187.5  425.76   195.4  425.64   275.2  425.83   287.2  427.19   315.1  441.28
     339  450.88     351  455.01     371   460.6   406.8  469.18   434.8  475.19
   482.6  483.04   510.6  486.81   566.4  496.23   682.1  511.79     710   514.4
#Mann= 4 ,-1 , 0
       0     .12       0  183.48     .04       0   187.5    .045       0
   275.2     .12       0
Bank Sta=187.5,275.2
XS Rating Curve= 0 ,0
Exp/Cntr=0.3,0.1

Type RM Length L Ch R = 1 ,8237.4  ,324,317.1,310.2
XS GIS Cut Line= 3
     2402685.426      342176.005     2402623.855      341800.538
     2402647.588      341578.627
#Sta/Elev= 30
       0  458.05    15.8   462.1    35.7  460.59    43.6  461.28    51.5  463.13
    63.4  464.41    91.2  462.05     107  462.72   118.9  460.14   150.6  457.64
   154.6  456.14   158.5  453.55   178.4  438.62   198.2  422.58  201.53418.7719
   206.1  415.42   210.1  416.32  216.02 418.615     218   419.6   237.8  436.48
   245.7  442.45   253.6  447.55   281.4  462.87   301.2  470.75   313.1  474.24
   356.7  484.29   416.4  494.63   444.2  498.69   492.1  504.18   603.7  515.17
#Mann= 3 ,-1 , 0
       0     .12       0  201.53    .045       0  216.02     .12       0
Bank Sta=201.53,216.02
XS Rating Curve= 0 ,0
Exp/Cntr=0.3,0.1

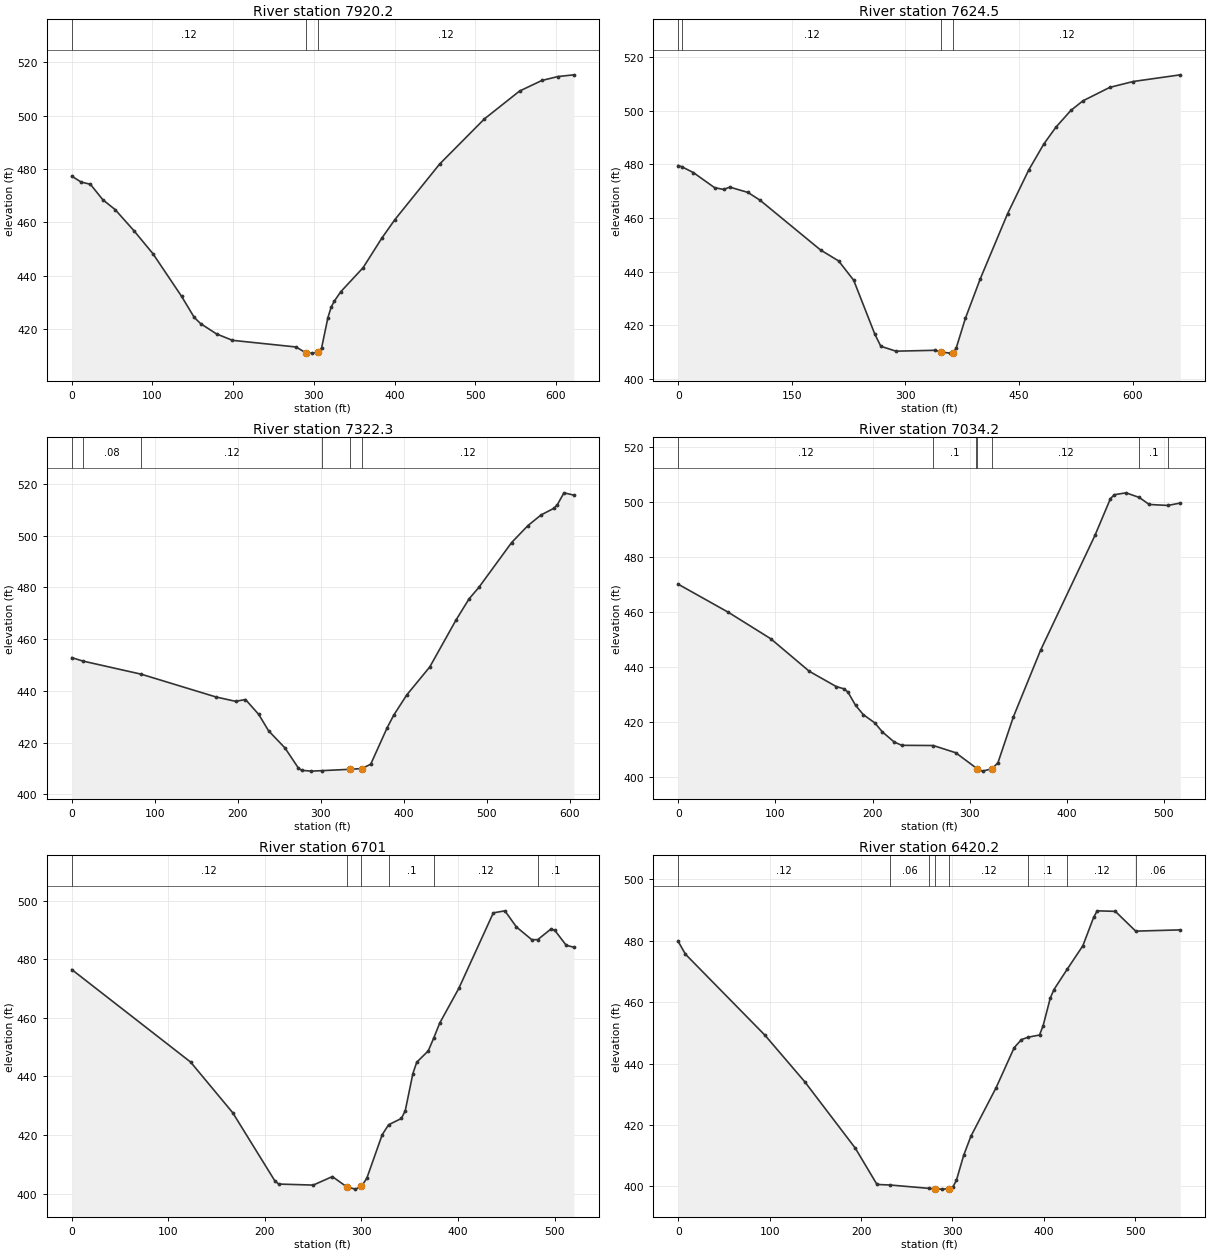
Type RM Length L Ch R = 1 ,7920.2  ,298.1,295.8,293.4
XS GIS Cut Line= 5
     2403110.395      342128.513     2403053.853      342076.422
     2402954.061      341879.463     2402895.155      341763.201
     2402885.696      341569.326
#Sta/Elev= 30
       0  477.32    11.5  475.11    23.1  474.26    38.4   468.5    53.8  464.76
    76.9  456.92   100.5  448.28     136   432.3   151.8  424.35   159.7  422.04
   179.4  418.18   199.1  415.79     278  413.29   290.2  411.06   297.7  410.99
   305.2  411.33   309.5  412.86   317.4  424.32   321.4  428.21   325.3  430.47
   333.2  433.97   360.9  442.98   384.6  454.28   400.4  461.04   455.7  481.81
   511.2  498.74   554.8  509.19   582.5  513.17   602.3  514.63   622.1  515.28
#Mann= 3 ,-1 , 0
       0     .12       0   290.2    .045       0   305.2     .12       0
Bank Sta=290.2,305.2
XS Rating Curve= 0 ,0
Exp/Cntr=0.3,0.1

Type RM Length L Ch R = 1 ,7624.5  ,297.4,302.2,307
XS GIS Cut Line= 4
     2403293.528       342053.21     2403315.291       341894.73
     2403105.625      341570.069     2402991.121      341548.259
#Sta/Elev= 30
       0  479.55    4.73479.0915      20  476.92      48  471.29      60  470.63
      68   471.5      92  469.52     108  466.62   187.9  448.05   211.8  443.96
   231.7  436.75   259.6  416.64   267.5  412.13   287.5  410.29   339.3  410.62
   347.6  409.95   359.2  409.56   363.2  409.63   367.2  411.56   379.1  422.48
     399   437.4   434.9  461.59   462.8  477.86   482.7  487.56   498.6  493.81
   518.6  500.15   534.5   503.7   569.8   508.7   600.8   510.9     663  513.39
#Mann= 4 ,-1 , 0
       0     .06       0    4.73     .12       0   347.6    .045       0
   363.2     .12       0
Bank Sta=347.6,363.2
XS Rating Curve= 0 ,0
Exp/Cntr=0.3,0.1

Type RM Length L Ch R = 1 ,7322.3  ,283.6,288,292.5
XS GIS Cut Line= 4
     2403499.695      341936.329     2403540.463      341755.479
     2403468.907      341566.163     2403563.704      341371.201
#Sta/Elev= 30
       0  452.84   13.41 451.511   83.64446.4354   173.6  437.63   197.3  435.94
   209.2  436.64   225.1   430.9     237  424.55   256.8  417.89   272.7  410.23
   276.7  409.26   288.6  408.95  301.39409.1368   334.5  409.65   349.5  409.96
     360  411.63   379.8  425.74   387.8  430.65   403.5  438.46   431.1  449.24
   462.7  467.38   478.4  475.56   490.3  480.04   529.7  497.36   549.4  503.93
   565.2  508.03   580.9  510.64   584.8  512.03   592.7  516.57   604.6  515.68
#Mann= 6 ,-1 , 0
       0     .12       0   13.41     .08       0   83.64     .12       0
  301.39     .08       0   334.5    .045       0   349.5     .12       0
Bank Sta=334.5,349.5
XS Rating Curve= 0 ,0
Exp/Cntr=0.3,0.1

Type RM Length L Ch R = 1 ,7034.2  ,337.8,333.2,328.7
XS GIS Cut Line= 4
     2403871.559      341834.633     2403773.594      341596.111
     2403757.969      341502.361     2403747.558      341338.757
#Sta/Elev= 30
       0  470.21    51.6  459.98    95.2  450.36   134.9   438.5   162.6  432.95
   170.6  432.11   174.6  430.97   182.5  426.13   190.4  422.75   202.3  419.71
   210.2   416.4   222.2  412.77   230.1  411.54  262.52411.4664   285.6  408.84
  306.21403.4099     308403.0334   313.3  402.14   323.1403.0274   329.1  405.21
     345  421.93   372.9  446.12   428.9  487.96   444.9   501.4   448.9   502.8
   460.9  503.49  474.52 501.813   484.8  499.25  504.06498.8948   516.8  499.78
#Mann= 7 ,-1 , 0
       0     .12       0  262.52      .1       0  306.21     .12       0
     308    .045       0   323.1     .12       0  474.52      .1       0
  504.06     .05       0
Bank Sta=308,323.1
XS Rating Curve= 0 ,0
Exp/Cntr=0.3,0.1

Type RM Length L Ch R = 1 ,6701    ,279.9,280.7,283.2
XS GIS Cut Line= 2
     2404158.465      341747.215     2403958.706      341267.104
#Sta/Elev= 30
       0  476.56   123.1  444.93   166.7  427.62   210.4  404.29   214.4  403.23
   250.1  402.88   269.9  405.79     285  402.23   293.8   401.5     300  402.42
   305.6  405.24   321.5   420.1  328.16423.5104   341.4  425.66   345.4  428.34
   353.3  441.01   357.3  444.89   369.2  448.75  375.08453.2971   381.1  458.28
   400.9  470.15   436.6  495.94   448.6  496.63   460.5  491.12   476.4  486.78
  482.53486.7671   496.2  490.39   500.2     490   512.1  484.85     520  484.19
#Mann= 6 ,-1 , 0
       0     .12       0     285    .045       0     300     .12       0
  328.16      .1       0  375.08     .12       0  482.53      .1       0
Bank Sta=285,300
XS Rating Curve= 0 ,0
Exp/Cntr=0.3,0.1

Type RM Length L Ch R = 1 ,6420.2  ,302.6,300,295.5
XS GIS Cut Line= 3
     2404412.148      341661.597     2404311.838      341391.067
     2404238.153      341141.052
#Sta/Elev= 30
       0  479.73     7.9  475.58    94.9   449.2   138.3   434.1   193.7  412.44
   217.4  400.63  231.95400.4469  274.27399.3579     281  399.15   288.5  399.11
     296  399.23   300.4   399.8   304.3     402   312.2  410.09   320.1   416.3
   347.8  432.19   367.5  445.17   375.4  447.78  382.64448.5548   395.2  449.28
   399.1  452.28     407  461.34     411  464.08  425.73470.8105   442.6  478.33
   454.4  487.58   458.3   489.7   478.1  489.53   500.4 483.092   549.2   483.5
#Mann= 8 ,-1 , 0
       0     .12       0  231.95     .06       0  274.27     .12       0
     281    .045       0     296     .12       0  382.64      .1       0
  425.73     .12       0   500.4     .06       0
Bank Sta=281,296
XS Rating Curve= 0 ,0
Exp/Cntr=0.3,0.1

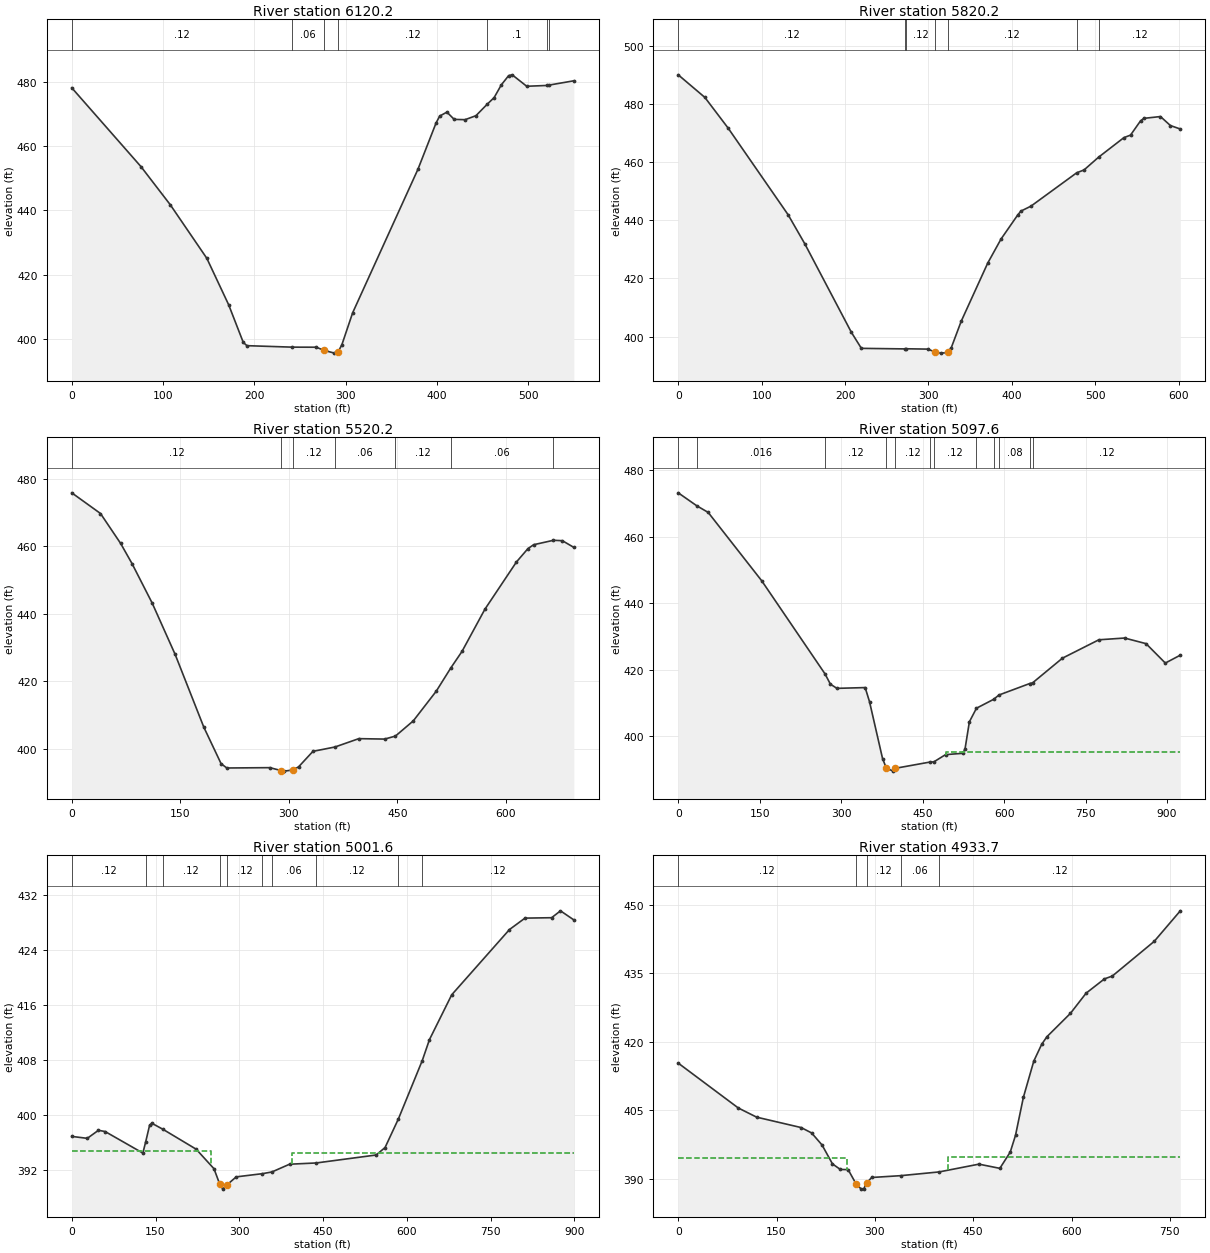
Type RM Length L Ch R = 1 ,6120.2  ,304.6,300,295.8
XS GIS Cut Line= 3
       2404702.3      341509.496     2404575.181       341255.81
     2404451.415      341020.254
#Sta/Elev= 30
       0  478.16    75.9  453.59   107.9  441.75   147.9  425.09   171.8  410.63
   187.8  398.92   191.8   397.9   241.2 397.444   267.8  397.42   276.3  396.43
   287.7  395.58   291.3  395.81   295.7  398.13   307.6  408.15   379.1  452.82
   398.9   467.2   402.9  469.37   410.8  470.59   418.8  468.33   430.7  468.24
   442.6  469.48  454.84473.0274   462.5  475.11   470.4  479.08   478.4  481.95
   482.3   482.2   498.2  478.64  520.37478.8906  522.14478.9833   549.8  480.34
#Mann= 7 ,-1 , 0
       0     .12       0   241.2     .06       0   276.3    .045       0
   291.3     .12       0  454.84      .1       0  520.37     .12       0
  522.14     .06       0
Bank Sta=276.3,291.3
XS Rating Curve= 0 ,0
Exp/Cntr=0.3,0.1

Type RM Length L Ch R = 1 ,5820.2  ,300.3,300,299.6
XS GIS Cut Line= 3
     2405014.009        341344.1     2404821.727      341094.134
     2404646.932        340866.9
#Sta/Elev= 30
       0  489.93    31.9  482.18    59.9   471.6   131.7  441.88   151.7  431.91
   207.6  401.47   219.6  395.96   271.5 395.772  273.66395.8152   299.4   395.7
   307.9  394.68   315.4  394.32   322.9  394.54   327.3  396.12   339.3  405.28
   371.1  425.26     387   433.5     407  441.76   410.9  443.12   422.9  444.81
  477.78 456.276   486.6  457.26  503.99461.6328   534.4  468.36   542.3  469.22
   554.3  474.11   558.2  474.97   578.2   475.6   590.1  472.51     602  471.31
#Mann= 7 ,-1 , 0
       0     .12       0   271.5     .06       0  273.66     .12       0
   307.9    .045       0   322.9     .12       0  477.78     .06       0
  503.99     .12       0
Bank Sta=307.9,322.9
XS Rating Curve= 0 ,0
Exp/Cntr=0.3,0.1

Type RM Length L Ch R = 1 ,5520.2  ,418.6,422.7,426.7
XS GIS Cut Line= 3
      2405249.82      341151.106     2405062.282      340914.919
     2404817.375      340608.482
#Sta/Elev= 30
       0  475.81    39.7  469.68    67.5  460.82    83.3  454.82   111.1  443.14
   142.9  427.89   182.5  406.33   206.4   395.5   214.3  394.23   273.8  394.33
   289.7  393.44   293.6   393.3   305.6  393.64   313.5  394.57   333.3  399.16
  363.86400.4601   396.7  402.93   432.4   402.8  447.34403.6917     472   408.2
   503.7  416.99  523.73423.8514   539.3  428.78     571  441.31   614.6  455.32
   630.5  459.28   638.4  460.43   665.7461.7364     678  461.62   693.9  459.63
#Mann= 7 ,-1 , 0
       0     .12       0   289.7    .045       0   305.6     .12       0
  363.86     .06       0  447.34     .12       0  523.73     .06       0
   665.7     .12       0
Bank Sta=289.7,305.6
XS Rating Curve= 0 ,0
Exp/Cntr=0.3,0.1

Type RM Length L Ch R = 1 ,5097.6  ,93.7,96,98.3
XS GIS Cut Line= 4
     2405371.339      341007.248     2405432.448      340741.944
     2405252.761      340407.309     2404980.625      340420.329
#Sta/Elev= 30
       0  473.27   33.91469.3908    55.2  467.36   153.9  446.73  270.24418.7278
   280.2  415.62   292.2  414.36   344.2  414.59   352.2  410.35   376.2  393.22
  383.29390.2807   396.2  389.42  399.09390.2509  463.58392.1555  470.64392.2044
   492.2  394.39   524.1  394.79   528.1  396.11   536.1  404.28  549.14408.3728
   580.9 411.066  590.47412.3466  647.31415.8185   652.5416.0205   707.4  423.45
   774.5  428.99   821.9  429.52   861.4  427.83   896.9  421.98   924.5  424.36
#Mann= 12 ,-1 , 0
       0     .08       0   33.91    .016       0  270.24     .12       0
  383.29    .045       0  399.09     .12       0  463.58     .06       0
  470.64     .12       0  549.14     .08       0   580.9     .12       0
  590.47     .08       0  647.31     .06       0   652.5     .12       0
#XS Ineff= 2 , 0
                           492.3          395.19
Permanent Ineff=
       F       F
Bank Sta=383.29,399.09
XS Rating Curve= 0 ,0
Exp/Cntr=0.3,0.1

Type RM Length L Ch R = 1 ,5001.6  ,67.9,67.9,67.9
XS GIS Cut Line= 3
     2405566.006      340843.895      2405364.74      340363.038
     2404988.438      340396.892
#Sta/Elev= 30
       0  396.88    27.8   396.6    47.8  397.77    59.7  397.59   127.3  394.46
  132.47396.1207   139.3  398.48   143.2   398.8  163.37397.9113   222.8  395.02
   254.7  392.18  264.77389.9826   270.6  389.22   278.6  389.89   294.5     391
  341.22391.4649  358.36 391.713     390  392.84  437.84393.0228   545.1  394.18
     561  395.26  585.05399.4478  627.69407.9102   640.6  410.96   680.4  417.46
   783.8  426.94   811.6   428.6   859.3  428.66   875.2  429.66   899.1  428.34
#Mann= 10 ,-1 , 0
       0     .12       0  132.47    .016       0  163.37     .12       0
  264.77    .045       0   278.6     .12       0  341.22    .016       0
  358.36     .06       0  437.84     .12       0  585.05     .06       0
  627.69     .12       0
#XS Ineff= 2 , 0
          248.71  394.78  395.25          394.53
Permanent Ineff=
       F       F
Bank Sta=264.77,278.6
XS Rating Curve= 0 ,0
Exp/Cntr=0.3,0.1

Type RM Length L Ch R = 1 ,4933.7  ,108.8,109.3,109.7
XS GIS Cut Line= 3
     2405621.986      340807.701     2405423.334       340333.09
     2405538.544      340109.651
#Sta/Elev= 30
       0  415.37    91.7  405.54   119.6  403.54   187.5  401.26   203.4  400.09
   219.4  397.44   235.3   393.3   247.3  392.09   259.2  392.04   271.2  388.95
   279.2  387.78   283.2  387.91   287.2  389.09   295.1  390.33  339.47390.7276
   398.2391.5508   458.7  393.25   490.6  392.33   506.5   395.9   514.5  399.56
   526.5  407.88   542.4  415.82   554.4  419.48   562.4  421.15   598.3  426.27
   622.2  430.69   650.2  433.82   662.2  434.44     726  442.02   765.9  448.72
#Mann= 5 ,-1 , 0
       0     .12       0   271.2    .045       0   287.2     .12       0
  339.47     .06       0   398.2     .12       0
#XS Ineff= 2 , 0
          256.76  394.66  411.15           394.9
Permanent Ineff=
       F       F
Bank Sta=271.2,287.2
XS Rating Curve= 0 ,0
Exp/Cntr=0.3,0.1

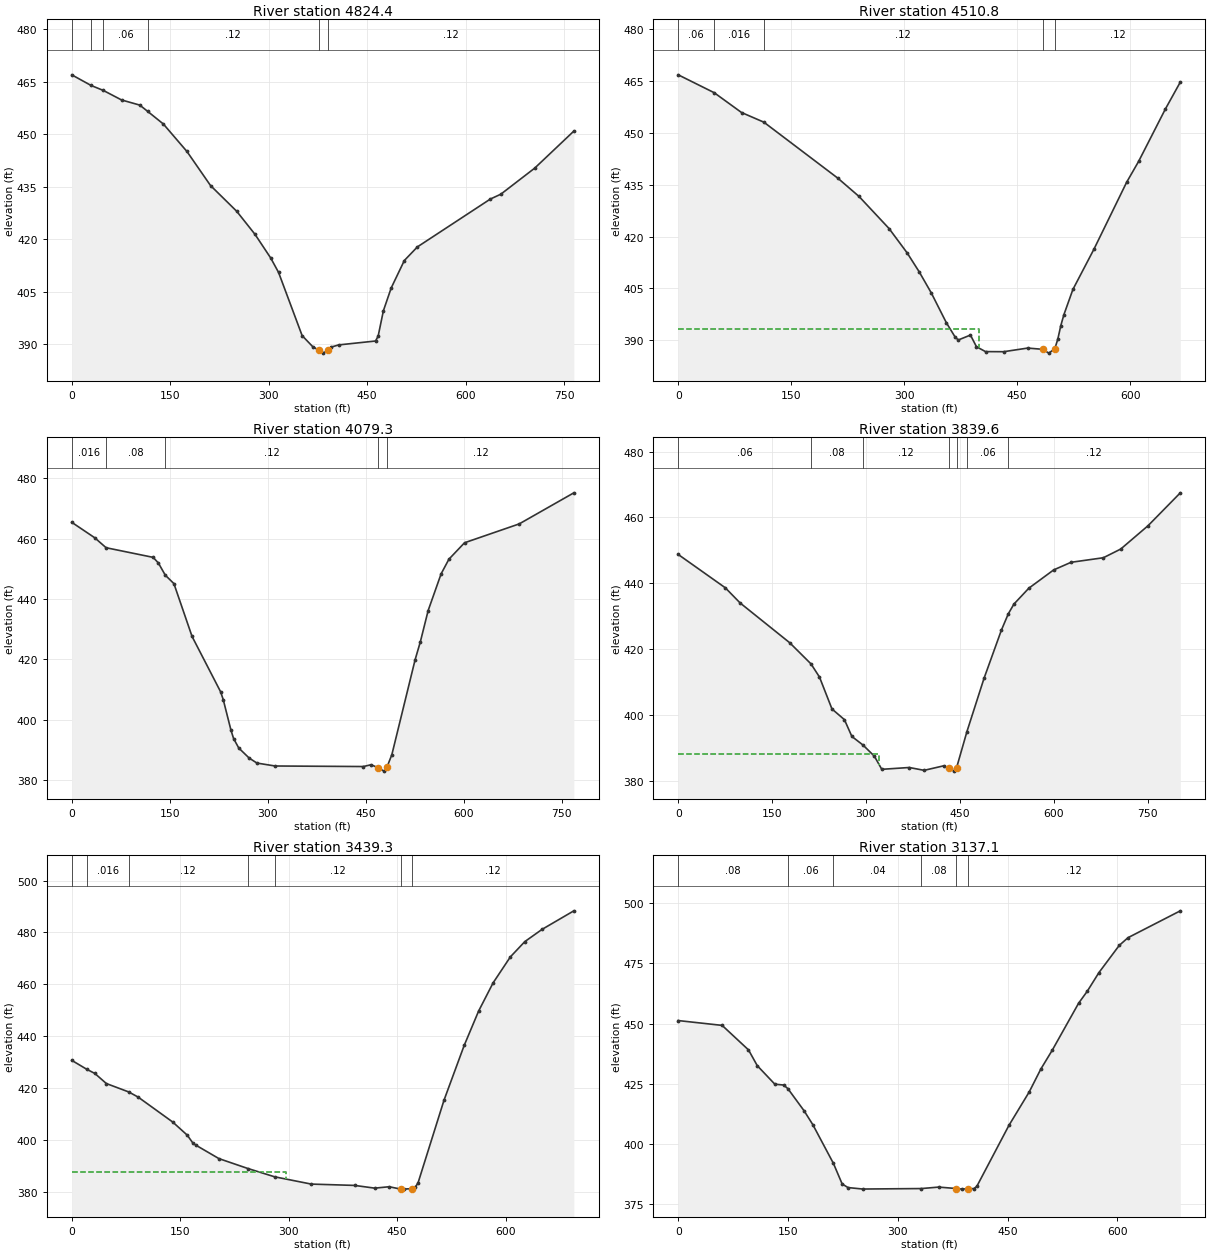
Type RM Length L Ch R = 1 ,4824.4  ,311,313.6,315.8
XS GIS Cut Line= 4
      2405834.13      340733.543     2405649.896      340629.965
     2405531.407      340329.184      2405573.93      340102.812
#Sta/Elev= 30
       0  466.99   29.49463.9489   48.16 462.524    75.8  459.82   103.7  458.34
  115.59 456.562   139.6  452.94   175.5   445.1   211.4  435.38   251.3  428.03
   279.2  421.44   303.2  414.66   315.1  410.56     351  392.52     367  389.39
     376  388.39     383  387.52     391   388.4   394.9  389.23   406.9  389.87
   462.8  390.98   466.8  392.35   474.8  399.61   486.7  406.13   506.7  413.96
   526.6  417.85   637.9  431.53   653.8  432.91   705.4  440.35     765  450.92
#Mann= 6 ,-1 , 0
       0     .06       0   29.49     .08       0   48.16     .06       0
  115.59     .12       0     376    .045       0     391     .12       0
Bank Sta=376,391
XS Rating Curve= 0 ,0
Exp/Cntr=0.3,0.1

Type RM Length L Ch R = 1 ,4510.8  ,411.1,431.5,451.9
XS GIS Cut Line= 3
     2405939.967      340721.579     2405772.292      340204.184
     2405778.803      340081.788
#Sta/Elev= 30
       0  466.73   47.77461.5593      84  455.84  113.67453.0479     212  436.84
     240  431.58   279.9   422.3   303.9  415.26   319.9  409.79   335.9  403.71
   355.9   395.1   367.9  390.83   371.9  390.11   387.9  391.52   395.9  388.15
   407.9  386.74   431.9  386.71   463.9  387.76   483.9   387.4   491.9   386.3
   499.9  387.55   503.9  390.37   507.9  394.28   511.9  397.37   523.9   404.7
   551.8  416.32   595.3   435.7   611.1  441.69   646.7  456.86   666.5  464.63
#Mann= 5 ,-1 , 0
       0     .06       0   47.77    .016       0  113.67     .12       0
   483.9    .045       0   499.9     .12       0
#XS Ineff= 2 , 0
          399.48  393.18
Permanent Ineff=
       F       F
Bank Sta=483.9,499.9
XS Rating Curve= 0 ,0
Exp/Cntr=0.3,0.1

Type RM Length L Ch R = 1 ,4079.3  ,256.4,239.7,222.9
XS GIS Cut Line= 4
     2405974.554      340717.669     2405981.928      340605.225
     2406243.646      340206.788      2406130.35      340067.631
#Sta/Elev= 30
       0  465.37      35  460.28    52.6456.9585   124.6  453.77   132.6  451.91
  143.16447.8889   156.4  445.08   184.2  427.59   227.9  409.28   231.9  406.72
   243.8  396.54   247.8   393.8   255.7  390.67   271.6  387.35   283.5  385.69
   311.3  384.72   446.4  384.54   458.3  385.13  468.64384.2022   478.2  383.02
  482.61384.3377   490.1  388.44   525.8  419.94   533.8  425.85   545.7  436.16
   565.6  448.34   577.5  453.16   601.4   458.6   685.1  464.84   768.8  475.13
#Mann= 5 ,-1 , 0
       0    .016       0    52.6     .08       0  143.16     .12       0
  468.64    .045       0  482.61     .12       0
Bank Sta=468.64,482.61
XS Rating Curve= 0 ,0
Exp/Cntr=0.3,0.1

Type RM Length L Ch R = 1 ,3839.6  ,389.4,400.3,410.6
XS GIS Cut Line= 4
     2406283.024      340742.116     2406397.292      340566.163
     2406355.625      340234.131     2406158.663      340067.471
#Sta/Elev= 30
       0  448.77    75.2  438.67      99  434.05   178.1  422.01   212.2 415.578
   225.7  411.61   245.7  401.91   265.6  398.67   277.5  393.58  295.32 390.964
   313.4   387.6   325.3  383.61   369.2  384.16     393   383.3   424.9   384.7
   432.9  383.92   440.9  383.06   444.8  384.06  461.43395.0737   488.7   411.2
   516.6  425.89  527.57430.8033   536.5  433.73   560.3  438.54     600  444.09
   627.8   446.4   679.4  447.78   707.2  450.42   750.8  457.49   802.4  467.47
#Mann= 7 ,-1 , 0
       0     .06       0   212.2     .08       0  295.32     .12       0
   432.9    .045       0   444.8     .12       0  461.43     .06       0
  527.57     .12       0
#XS Ineff= 2 , 0
          320.95  388.11
Permanent Ineff=
       F       F
Bank Sta=432.9,444.8
XS Rating Curve= 0 ,0
Exp/Cntr=0.3,0.1

Type RM Length L Ch R = 1 ,3439.3  ,315.8,302.1,288.6
XS GIS Cut Line= 2
     2406601.749      340789.911     2406837.046      340136.469
#Sta/Elev= 30
       0  430.74   20.76 427.295    31.9   425.7    47.9   421.8   78.74418.5778
    91.8  416.59   139.7  406.97   159.7  401.94   167.6  398.87   171.6  398.08
   203.6  392.89  243.62389.0804  280.67385.8838   331.3  383.08   391.2  382.57
   419.1  381.52   439.1  382.06     455  381.15     459  381.14     471  381.35
     475  381.82     479  383.56   514.9  415.39   542.8  436.48   562.8  449.74
   582.8  460.58   606.7  470.59   626.7  476.48   650.6   481.2   694.5  488.33
#Mann= 7 ,-1 , 0
       0     .12       0   20.76    .016       0   78.74     .12       0
  243.62     .06       0  280.67     .12       0     455    .045       0
     471     .12       0
#XS Ineff= 2 , 0
          296.18   387.7
Permanent Ineff=
       F       F
Bank Sta=455,471
XS Rating Curve= 0 ,0
Exp/Cntr=0.3,0.1

Type RM Length L Ch R = 1 ,3137.1  ,231.4,233.5,235.2
XS GIS Cut Line= 3
     2407137.345      340815.401     2407031.407      340400.798
     2407027.822      340142.726
#Sta/Elev= 30
       0  451.24      60  449.23      96  439.03     108  432.45     132  424.75
     144   424.4  149.76422.9148     172  413.66     184  407.84  212.06391.7605
     224  383.19     232  381.71     252   381.1  332.29381.2988   355.9  381.91
   379.9  381.31   387.9  381.06   395.9  381.25   403.9  381.27   407.9  382.18
   451.8  407.58   479.5   421.5   495.4  431.04   511.3  439.04     547  458.44
     559  463.51   574.8  471.21   602.6  482.55   614.6  485.76     686  496.93
#Mann= 6 ,-1 , 0
       0     .08       0  149.76     .06       0  212.06     .04       0
  332.29     .08       0   379.9    .045       0   395.9     .12       0
Bank Sta=379.9,395.9
XS Rating Curve= 0 ,0
Exp/Cntr=0.3,0.1

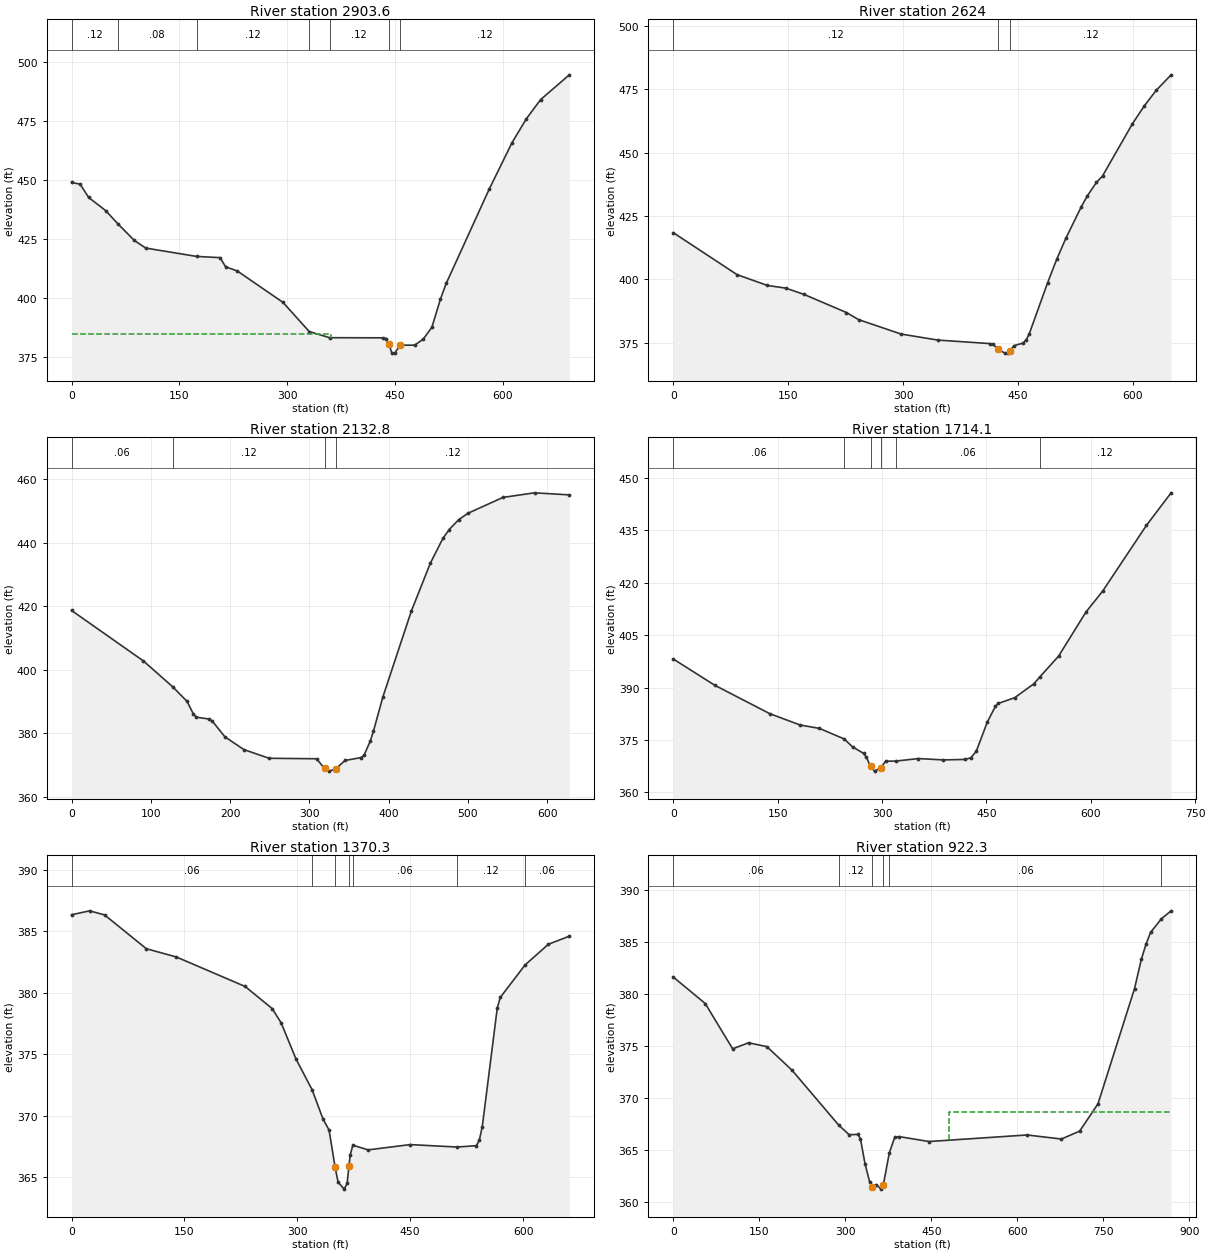
Type RM Length L Ch R = 1 ,2903.6  ,276.7,279.6,282.5
XS GIS Cut Line= 3
     2407211.424      340795.141     2407309.707      340665.462
     2407221.357      340142.726
#Sta/Elev= 30
       0  449.03    11.9  448.32    23.8  442.67    47.6  437.08   64.42431.4994
    87.3  424.46   103.2   421.2  174.02 417.657   206.6  417.14   214.5  413.24
   230.5  411.52   294.3  398.16  330.82 385.783   359.2 383.177   433.8  383.12
   437.8  382.81   441.7  380.31   445.7  376.81   449.7  376.63   457.7  380.01
   477.6  380.01   489.6   382.6   501.5  387.56   513.5  399.58   521.5  406.21
   581.2   446.1   613.1  465.92   633.1  476.07     653  484.22   692.9   494.7
#Mann= 7 ,-1 , 0
       0     .12       0   64.42     .08       0  174.02     .12       0
  330.82     .04       0   359.2     .12       0   441.7    .045       0
   457.7     .12       0
#XS Ineff= 2 , 0
           361.2  384.83
Permanent Ineff=
       F       F
Bank Sta=441.7,457.7
XS Rating Curve= 0 ,0
Exp/Cntr=0.3,0.1

Type RM Length L Ch R = 1 ,2624    ,463.6,491.2,488.4
XS GIS Cut Line= 4
     2407455.932      340758.801     2407532.371      340458.975
     2407521.091      340208.027      2407456.88       340145.71
#Sta/Elev= 30
       0  418.43    83.3  401.88     123  397.61   146.8  396.58   170.6  394.11
   226.1  386.95     242  384.15   297.5  378.46   345.3  376.09   413.1  374.71
   417.1  374.51   424.6  372.41     433  370.94     437  371.04   439.6  371.83
     445  373.89     457  374.93   460.9  376.18   464.9  378.59   488.8  398.67
   500.8     408   512.8  416.33   532.7  428.58   540.7  432.95   552.6  438.24
   560.6  440.83   599.5  461.33   615.1  468.43   630.6  474.54   650.1  480.68
#Mann= 3 ,-1 , 0
       0     .12       0   424.6    .045       0   439.6     .12       0
Bank Sta=424.6,439.6
XS Rating Curve= 0 ,0
Exp/Cntr=0.3,0.1

Type RM Length L Ch R = 1 ,2132.8  ,430.9,418.7,405.4
XS GIS Cut Line= 3
     2407812.587      340779.056     2407825.678      340626.059
     2407967.454      340173.416
#Sta/Elev= 30
       0  418.65    90.6  402.78  127.79394.5945   145.7  390.06   153.6   386.1
   157.5  385.08   173.5   384.5   177.5  383.87   193.4  378.92   217.3   374.9
   249.2  372.16     309  372.01  319.06368.9722     325  368.12   333.5  368.86
   344.9  371.47   364.8  372.36   368.8  373.05   376.8  377.57   380.8  380.68
   392.7  391.46   428.6  418.46   452.5  433.48   468.4  441.31   476.4  444.11
   488.4  447.23   500.3  449.25   544.2  454.21     584  455.65   627.9     455
#Mann= 4 ,-1 , 0
       0     .06       0  127.79     .12       0  319.06    .045       0
   333.5     .12       0
Bank Sta=319.06,333.5
XS Rating Curve= 0 ,0
Exp/Cntr=0.3,0.1

Type RM Length L Ch R = 1 ,1714.1  ,334.7,343.9,352.3
XS GIS Cut Line= 4
     2408158.766      340770.937     2408255.365      340549.236
     2408198.269      340323.268     2408005.365      340179.444
#Sta/Elev= 30
       0  398.16    59.5  390.66   138.8   382.5   182.4  379.26   210.1  378.29
   245.6 375.271   257.6  373.01   273.4  371.15   277.4  370.09   283.5   367.4
   289.2  366.06   298.5  367.04     305   368.9  319.51368.9331   352.4  369.66
     388  369.27   419.6  369.41   427.5  369.88   435.4  371.71   451.2  380.04
     463  384.64     467  385.43   490.7  387.09   518.3  391.07  526.55392.9782
   553.8     399   593.2  411.64   616.9  417.54     680  436.42   715.5  445.75
#Mann= 6 ,-1 , 0
       0     .06       0   245.6     .12       0   283.5    .045       0
   298.5     .12       0  319.51     .06       0  526.55     .12       0
Bank Sta=283.5,298.5
XS Rating Curve= 0 ,0
Exp/Cntr=0.3,0.1

Type RM Length L Ch R = 1 ,1370.3  ,434.1,447.9,459.2
XS GIS Cut Line= 3
     2408425.744      340763.225     2408558.976      340500.798
      2408592.36       340135.09
#Sta/Elev= 30
       0  386.34    23.9  386.66    43.8  386.33    99.4  383.58   139.2  382.91
   230.7  380.51   266.5  378.72   278.4  377.57   298.3  374.61   319.6372.1234
   334.2  369.73   342.2  368.84   350.2  365.83   354.2  364.61   362.2  364.04
   366.2   364.5   368.7365.9375   370.2   366.8   373.8367.6127   394.1  367.23
     450  367.66  512.03367.4619   537.8  367.57   541.8     368   545.8  369.12
   565.7  378.75   569.7  379.62  602.73382.2647   633.6  383.94   661.5   384.6
#Mann= 7 ,-1 , 0
       0     .06       0   319.6     .12       0   350.2    .045       0
   368.7     .12       0   373.8     .06       0  512.03     .12       0
  602.73     .06       0
Bank Sta=350.2,368.7
XS Rating Curve= 0 ,0
Exp/Cntr=0.3,0.1

Type RM Length L Ch R = 1 ,922.3   ,239.2,246.3,255.1
XS GIS Cut Line= 3
     2408636.987      340829.021     2409071.129      340419.201
     2408919.782      340194.263
#Sta/Elev= 30
       0  381.61    55.7  379.07   103.5  374.72   131.3   375.3   163.2  374.93
     207  372.67  288.76367.3772   306.5  366.48   322.4   366.5   326.4  366.06
   334.3   363.7   342.3  361.96   346.3   361.5   354.2  361.68   362.2  361.25
   366.2  361.65  376.76364.7443   386.1  366.22     394  366.29   445.8  365.82
     617  366.45   676.8  366.06   708.6  366.82   740.6  369.44   804.3   380.5
   816.3  383.33   824.3  384.76   832.2  385.89   851.2387.2075   868.1  387.97
#Mann= 6 ,-1 , 0
       0     .06       0  288.76     .12       0   346.3    .045       0
   366.2     .12       0  376.76     .06       0   851.2     .12       0
#XS Ineff= 2 , 0
                          480.91          368.61
Permanent Ineff=
       F       F
Bank Sta=346.3,366.2
XS Rating Curve= 0 ,0
Exp/Cntr=0.3,0.1