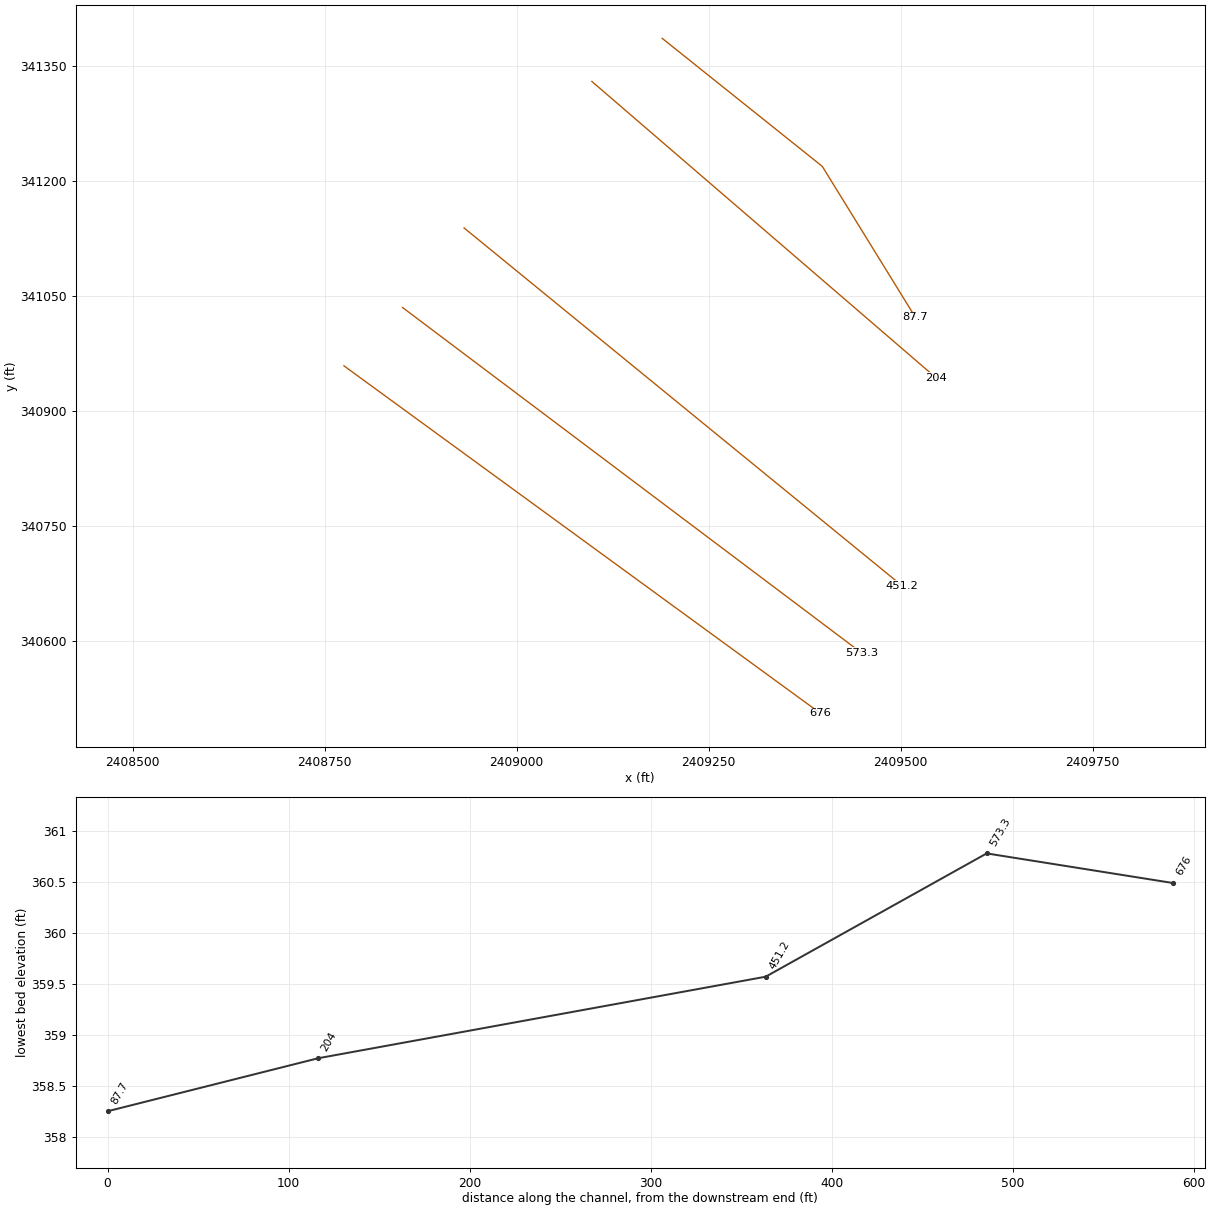
HEC-RAS study EVANSRUN2.prj: EVANSRUN2

--- EVANSRUN2.g01 (geometry) --- (continued)

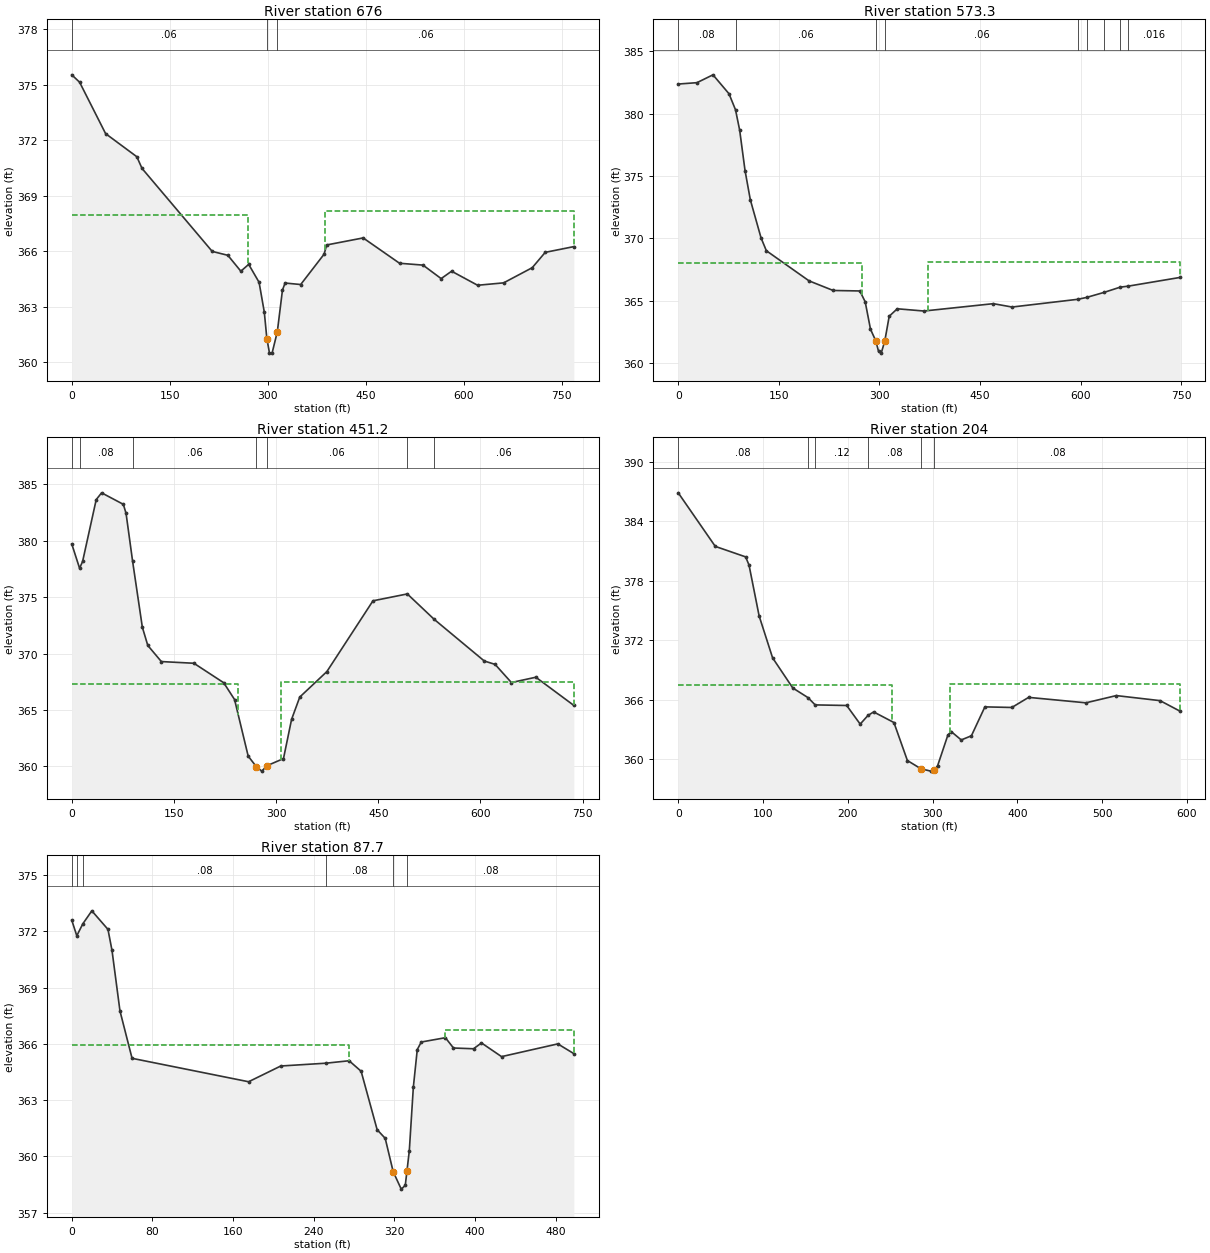
Type RM Length L Ch R = 1 ,676     ,103.2,102.7,102.4
XS GIS Cut Line= 2
      2408775.06      340958.892     2409395.665      340505.597
#Sta/Elev= 30
       0  375.54      12  375.14    51.8  372.36    99.6  371.11   107.5  370.48
     215  365.99   238.9  365.78   258.8  364.92   270.8  365.29   286.7  364.32
   294.7  362.71   298.6  361.28   302.6   360.5   306.6  360.49   314.6  361.64
   322.5   363.9   326.5  364.28   350.4   364.2   386.2  365.84   390.2  366.34
     446  366.72   501.7  365.35   537.6  365.25   565.4  364.52   581.4  364.92
   621.2  364.16     661  364.29   704.8  365.11   724.7  365.94   768.5  366.25
#Mann= 3 ,-1 , 0
       0     .06       0   298.6    .045       0   314.6     .06       0
#XS Ineff= 2 , 0
          269.97  367.97  388.03          368.19
Permanent Ineff=
       F       F
Bank Sta=298.6,314.6
XS Rating Curve= 0 ,0
Exp/Cntr=0.3,0.1

Type RM Length L Ch R = 1 ,573.3   ,122.9,122.1,121.1
XS GIS Cut Line= 2
     2408851.375      341034.971     2409449.284      340584.339
#Sta/Elev= 30
       0  382.38    27.9  382.49    51.8  383.12    75.7   381.6   85.42380.3106
    91.6  378.68    99.6  375.44   107.5  373.09   123.5  370.03   131.4     369
   195.1  366.58     231  365.81   270.8  365.77   278.8   364.9   286.7   362.7
   294.7  361.75   298.7  360.92   302.7  360.78     308361.7505   314.6  363.74
   326.6  364.34   366.4  364.16   469.9  364.75   497.8  364.48  596.09365.1029
  608.83365.2488  634.87365.6534  658.97366.0747  671.38  366.16   748.7  366.86
#Mann= 9 ,-1 , 0
       0     .08       0   85.42     .06       0   294.7    .045       0
     308     .06       0  596.09    .016       0  608.83     .06       0
  634.87    .016       0  658.97     .06       0  671.38    .016       0
#XS Ineff= 2 , 0
           274.1  367.98  372.34          368.11
Permanent Ineff=
       F       F
Bank Sta=294.7,308
XS Rating Curve= 0 ,0
Exp/Cntr=0.3,0.1

Type RM Length L Ch R = 1 ,451.2   ,247.7,247.2,247.4
XS GIS Cut Line= 2
      2408931.45      341138.795     2409501.905      340672.059
#Sta/Elev= 30
       0  379.72   11.47377.5684    15.9  378.17    35.9  383.66    43.8  384.26
    75.7  383.24    79.7  382.44   89.34378.1748   103.6  372.34   111.6  370.72
   131.5  369.29   179.3  369.14   223.1  367.41     239  365.92     259   360.9
   270.9  359.97   278.9  359.57   286.9  360.06   310.8  360.68   322.7  364.16
   334.7  366.14   374.5   368.4   442.2  374.68  492.61375.2904  532.04373.0377
   605.6  369.34   621.5  369.04   645.4  367.43   681.3   367.9   737.1   365.4
#Mann= 7 ,-1 , 0
       0     .06       0   11.47     .08       0   89.34     .06       0
   270.9    .045       0   286.9     .06       0  492.61    .016       0
  532.04     .06       0
#XS Ineff= 2 , 0
          244.38  367.31  307.12          367.52
Permanent Ineff=
       F       F
Bank Sta=270.9,286.9
XS Rating Curve= 0 ,0
Exp/Cntr=0.3,0.1

Type RM Length L Ch R = 1 ,204     ,123.3,116.3,108.6
XS GIS Cut Line= 2
      2409097.94       341329.83     2409546.389      340943.072
#Sta/Elev= 30
       0  386.88    43.7  381.47    79.5  380.41    83.5  379.58    95.4  374.45
   111.3  370.21   135.1  367.17  153.06366.1936  161.53365.4592   198.7   365.4
   214.6  363.52  223.79364.3929   230.5  364.75   254.4  363.68   270.3  359.84
   286.2  359.01   297.8  358.77   302.1  358.88     306  359.33     318   362.4
   321.9  362.77   333.8  361.92   345.8  362.34   361.7  365.26   393.5   365.2
   413.3  366.22   480.9  365.67   516.7   366.4   568.3  365.89   592.2  364.81
#Mann= 6 ,-1 , 0
       0     .08       0  153.06     .06       0  161.53     .12       0
  223.79     .08       0   286.2    .045       0   302.1     .08       0
#XS Ineff= 2 , 0
          252.63  367.42  320.12          367.53
Permanent Ineff=
       F       F
Bank Sta=286.2,302.1
XS Rating Curve= 0 ,0
Exp/Cntr=0.3,0.1

Type RM Length L Ch R = 1 ,87.7    ,102.7,87.7,72.3
XS GIS Cut Line= 3
     2409189.491      341386.096     2409397.952      341219.114
     2409519.046        341022.5
#Sta/Elev= 30
       0   372.6    4.98371.7698   10.96372.4068    19.9   373.1    35.9  372.11
    39.9  370.99    47.8  367.76    59.8  365.23   175.4  363.98   207.3  364.82
  252.02364.9695   275.1   365.1     287  364.54   302.9  361.42   310.9  360.96
   318.8  359.18   326.8  358.25   330.8  358.45  332.42359.1965   334.8   360.3
   338.8  363.69   342.7   365.7   346.7   366.1   370.6  366.33   378.6  365.78
   398.5  365.74   406.4  366.05   426.3  365.32   482.1     366     498  365.48
#Mann= 6 ,-1 , 0
       0     .12       0    4.98     .06       0   10.96     .08       0
  252.02     .08       0   318.8    .045       0  332.42     .08       0
#XS Ineff= 2 , 0
          275.03  365.95  369.97          366.73
Permanent Ineff=
       F       F
Bank Sta=318.8,332.42
XS Rating Curve= 0 ,0
Exp/Cntr=0.3,0.1

Chan Stop Cuts=-1
Use User Specified Reach Order=0
Composite Channel Slope=5